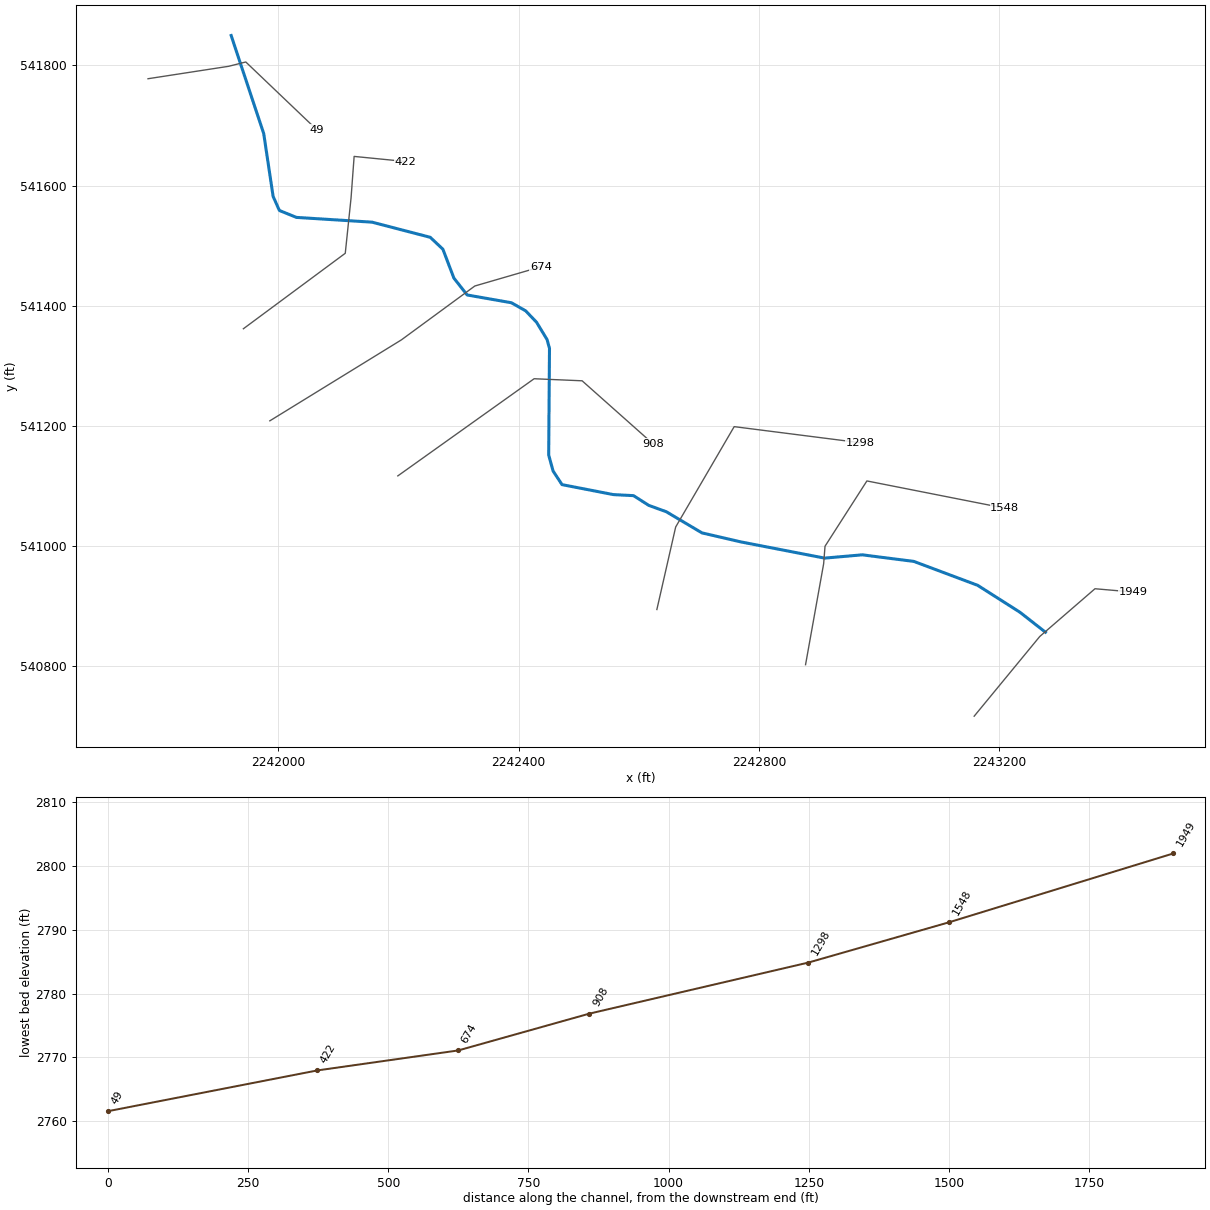
--- TYGVRV2T5.prj (project) ---

Proj Title=TYGVRV2T5
Current Plan=p01
Default Exp/Contr=0,0
English Units
Geom File=g01
Flow File=f01
Plan File=p01
BEGIN DESCRIPTION:
----------MODEL BY WOOD PLC 2022----------
AFH study
Randolph County, WV
HEC-RAS Version: RAS 6.2
Vertical Datum: NAVD88
Projection: NAD 1983 StatePlane West Virginia S FIPS 4702 (US Feet)
Terrain: 1-meter LIDAR (FEMA Region III 3DEP collected 2016-2018)
Land Use: 2019 NLCD
Hydrologic Method:
WV SIR2010-5033 regression equations
Additional Model Notes:
Dominant flow path issue with TYGVRV2T5, as it has a smaller DA than TYGVRV2T5ATYGVRV2T5A had a higher DA than TYGVRV2T5, so the flow paths were switched and the names were switched
END DESCRIPTION:
DSS Export Rating Curves= 0
DSS Export Rating Curve Sorted= 0
DSS Export Volume Flow Curves= 0
DXF OffsetX= 0
DXF OffsetY= 0
DXF ScaleX= 0
DXF ScaleY= 0

--- TYGVRV2T5.p01 (plan) ---

Plan Title=Floodplain
Program Version=6.20
Short Identifier=Floodplain
Geom File=g01
Flow File=f01
Subcritical Flow
K Sum by GR= 0
Std Step Tol= 0.01
Critical Tol= 0.01
Num of Std Step Trials= 20
Max Error Tol= 0.3
Flow Tol Ratio= 0.001
Split Flow NTrial= 30
Split Flow Tol= 0.02
Split Flow Ratio= 0.02
Log Output Level= 0
Friction Slope Method= 1
Unsteady Friction Slope Method= 2
Unsteady Bridges Friction Slope Method= 1
Parabolic Critical Depth
Global Vel Dist= 0 , 0 , 0
Global Log Level= 0
CheckData=True
Encroach Param=-1 ,0,0, 0
Mapping Interval=1HOUR
Computation Time Step Use Courant=        0
Computation Time Step Use Time Series=    0
Computation Time Step Count To Double=0
Computation Time Step Max Doubling=0
Computation Time Step Max Halving=0
Computation Time Step Residence Courant=0
Run HTab= 0
Run UNet= 0
Run Sediment= 0
Run PostProcess= 0
Run WQNet= 0
Run RASMapper=-1
UNET Theta= 0
UNET Theta Warmup= 0
UNET ZTol= 0
UNET ZSATol= 0
UNET MxIter= 0
UNET Max Iter WO Improvement= 0
UNET MaxInSteps= 0
UNET DtIC= 0
UNET DtMin= 0
UNET MaxCRTS= 0
UNET WFStab= 0
UNET SFStab= 0
UNET WFX= 1
UNET SFX= 1
UNET Gravity=32.174
UNET 1D Methodology=Finite Difference
UNET DSS MLevel= 1
UNET Pardiso=0
UNET DZMax Abort= 0
UNET Use Existing IB Tables= 0
UNET Froude Reduction=False
UNET Froude Limit= 0
UNET Froude Power= 0
UNET D1 Cores= 0
UNET WindReference=Eulerian
UNET WindDragFormulation=Hsu (1988)
UNET D2 Coriolis=0
UNET D2 Cores= 0
UNET D2 Theta= 1
UNET D2 Theta Warmup= 1
UNET D2 Z Tol= 0.01
UNET D2 Volume Tol= 0.01
UNET D2 Max Iterations= 20
UNET D2 Equation= 0
UNET D2 RampUpFraction=0.1
UNET D2 TimeSlices= 1
UNET D2 Turbulence Formulation=Non-Conservative (original)
UNET D2 Eddy Viscosity=0.3
UNET D2 Transverse Eddy Viscosity=0.1
UNET D2 Smagorinsky Mixing=0
UNET D2 BCVolumeCheck=0
UNET D2 Cores=0
UNET D2 SolverType=PARDISO (Direct)
UNET D2 Minimum Iterations= 2147483647
UNET D2 Maximum Iterations= 2147483647
UNET D2 Restart Number= 10
UNET D2 Relaxation Coeff=1.3
UNET D2 SOR Precondition Iterations= 10
UNET D2 ILUT Maximum Fill= 8
UNET D2 ILUT Tolerance=1E-08
UNET D1D2 MaxIter= 0
UNET D1D2 ZTol=0.01
UNET D1D2 QTol=0.1
UNET D1D2 MinQTol=1
Write IC File= 0
Write IC File at Fixed DateTime=0
Write IC File at Sim End=0
Echo Input=False
Echo Parameters=False
Echo Output=False
Write Detailed= 0
HDF Write Warmup=0
HDF Write Time Slices=0
HDF Flush=0
HDF Compression= 1
HDF Chunk Size= 1
HDF Spatial Parts= 1
HDF Use Max Rows=0
HDF Fixed Rows= 1
Calibration Method= 0
Calibration Iterations= 20
Calibration Max Change=0.05
Calibration Tolerance=0.2
Calibration Maximum=1.5
Calibration Minimum=0.5
Calibration Optimization Method= 1
WQ AD Non Conservative
WQ ULTIMATE=-1
WQ Max Comp Step=1HOUR
WQ Output Interval=15MIN
WQ Output Selected Increments= 0
WQ Output face flow=0
WQ Output face velocity=0
WQ Output face area=0
WQ Output face dispersion=0
WQ Output cell volume=0
WQ Output cell surface area=0
WQ Output cell continuity=0
WQ Output cumulative cell continuity=0
WQ Output face conc=0
WQ Output face dconc_dx=0
WQ Output face courant=0
WQ Output face peclet=0
WQ Output face adv mass=0
WQ Output face disp mass=0
WQ Output cell mass=0
WQ Output cell source sink temp=0
WQ Output nsm pathways=0
WQ Output nsm derived pathways=0
WQ Create Restart=0
WQ Fixed Restart=0
WQ System Summary=0
WQ Write To DSS=0
Sorting and Armoring Iterations= 10
XS Update Threshold= 0.02
Bed Roughness Predictor= 0
Hydraulics Update Threshold= 0.02
Energy Slope Method= 1
Volume Change Method= 1
Sediment Retention Method= 0
Sediment TS Multiplier= 1
Warm Up Method= 0
XS Weighting Method= 0
Number of US Weighted Cross Sections= 1
Number of DS Weighted Cross Sections= 1
Upstream XS Weight=0
Main XS Weight=1
Downstream XS Weight=0
Number of DS XS's Weighted with US Boundary= 1
Upstream Boundary Weight= 1
Weight of XSs Associated with US Boundary= 0
Number of US XS's Weighted with DS Boundary= 1
Downstream Boundary Weight= 0.5
Weight of XSs Associated with DS Boundary= 0.5
Percentile Method= 0
Sediment Output Level= 3
Mass or Volume Output= 0
Output Increment Type= 1
Profile and TS Output Increment= 1
Transport Output Increment 1
XS Output Flag= 0
XS Output Increment= 10
Read HDF5 Sediment Hotstart= 0
Sediment Hotstart Type= 0
Write Gradation File= 0
Read Gradation Hotstart= 0
Write HDF5 File= 1
Write Binary Output= 1
Write DSS Sediment File= 0
DSS Sediment Output Type= 1
SV Curve= 0
Specific Gage Flag= 0
Subcell Erosion Methods= 0
Subcell Deposition Methods= 0
Advection Scheme= 1
Matrix Solver= 0
Implicit Weighting Factor= 1
Maximum Outer Loop Convergence Iterations= 5
Convergence Maximum Absolute= 0.001
Convergence RMSE= 0.0001
Grain Fractions Max Abs Error= 0.001
Max Subgrid Regions= 1
Max Subgrid Length Scale= 3.402823E+38
Initial Layer Thickness= 3.402823E+38
Min Layer Thickness= 3.402823E+38
Max Layer Thickness= 3.402823E+38
Number of Layers= 5

--- TYGVRV2T5.f01 (steady flow) ---

Flow Title=Flow
Program Version=6.20
Number of Profiles= 1
Profile Names=P100yr
River Rch & RM=TYGVRV2T5A,Main            ,1949
     298
River Rch & RM=TYGVRV2T5A,Main            ,674
     301
River Rch & RM=TYGVRV2T5,Main            ,1949
     298
River Rch & RM=TYGVRV2T5,Main            ,674
     301
Boundary for River Rch & Prof#=TYGVRV2T5,Main            , 1
Up Type= 0
Dn Type= 3
Dn Slope=0.01714
DSS Import GetInterval= 0
DSS Import GetPeak= 0
DSS Import FillOption= 0

--- TYGVRV2T5.g01 (geometry) ---

Geom Title=Geometry
Program Version=6.20

River Reach=TYGVRV2T5       ,Main
Reach XY= 30
2243276.90800002540856.492000014     2243234.543540889.643000007
2243164.08100002 540934.549000012243057.84100005 540974.34300001
2242972.04600005540985.2960000192242909.25099999540979.819999993
2242769.78800003541006.8359999952242705.16800001541021.805000022
2242645.70197496541057.0623537152242616.61955462541067.602291301
2242591.24563082541083.8025657242242557.67397784541085.559221968
2242472.18337308541102.1498644652242457.29260765541124.780281305
     2242449.973541151.4099999962242451.31299999541328.991000012
2242447.24600002541343.6400000012242429.82800001541372.399000019
2242411.61900003 541391.483000012242387.87400001541404.934000015
2242314.24842682541417.8674050722242292.17699999541445.939999998
     2242273.844541494.0859999952242252.74499999541513.892000005
2242155.94400001541539.0820000172242030.04000002541546.994000018
2242001.66800003541558.5500000122241991.22900002541582.006000012
2241975.58200002541686.5620000212241921.39100002541849.778999999

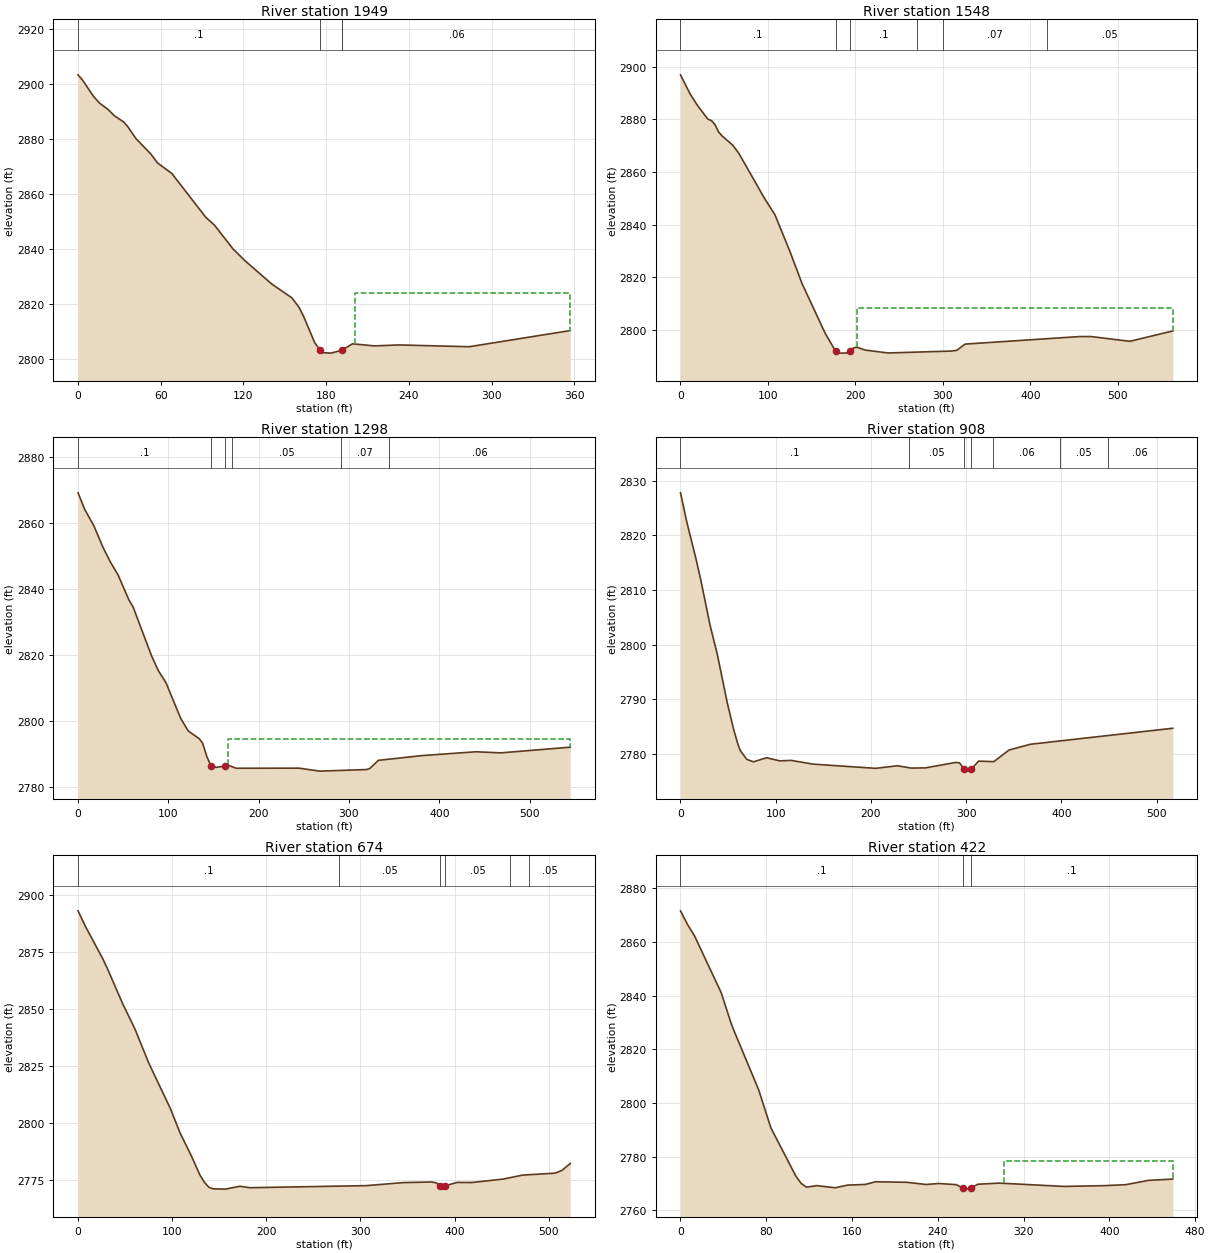
Type RM Length L Ch R = 1 ,1949    ,395.7,400.5,407.7
XS GIS Cut Line= 4
2243158.26916781 540716.683500952243267.46114689540849.372488192
 2243359.3759141540928.8476628422243422.95605382 540923.31895504
#Sta/Elev= 30
       0 2903.26       3 2901.54      11  2895.6    15.6 2892.95    21.4 2890.83
    26.5 2888.32      33 2886.15    35.8  2884.6    42.1 2880.01    52.9 2874.42
    57.6 2871.23      68 2867.41    92.6 2851.49    99.1 2848.52   112.5 2839.89
   121.1 2835.65   140.5 2827.18   155.2 2822.12   160.4 2818.65   163.7 2815.34
   171.8 2805.74  175.872803.006   177.9 2802.17   183.4 2802.01  191.182803.012
   199.2  2805.4   215.1 2804.64   232.7 2804.99   283.8 2804.34   357.2 2810.22
#Mann= 4 ,-1,0
       0      .1       0  175.87    .045       0  191.18      .1       0
  191.84     .06       0
#XS Ineff= 2 , 0
                           201.3         2823.79
Permanent Ineff=
       F       F
Bank Sta=175.87,191.18
XS Rating Curve= 0 ,0
Exp/Cntr(USF)=0,0
Exp/Cntr=0.3,0.1

Type RM Length L Ch R = 1 ,1548    ,253.2,250.4,246.1
XS GIS Cut Line= 5
2242877.56212858540802.4120454422242907.68802567540970.416817331
2242909.97969056540999.5900919052242979.67589632 541108.29898881
2243209.06149426541063.006337267
#Sta/Elev= 30
       0 2896.95    10.9 2889.75    19.1 2885.48    31.3 2880.09    35.3 2879.58
    39.4 2878.07    43.4 2875.35    47.5 2873.73    59.7 2870.22    66.7 2867.13
    96.3 2849.87     108 2843.76   124.7 2830.18     139 2817.62   165.4 2798.75
   177.5 2791.83   181.5 2791.19   189.5 2791.23  194.182791.923   197.5 2793.14
   201.8 2793.43   211.3 2792.34   237.4 2791.25   309.8 2791.98   315.9 2792.25
   325.4 2794.62     456 2797.48   469.1  2797.5   513.7 2795.68   562.9 2799.62
#Mann= 6 ,-1,0
       0      .1       0   177.5    .045       0  194.18      .1       0
  269.95     .06       0  299.95     .07       0  419.08     .05       0
#XS Ineff= 2 , 0
                          201.49         2808.21
Permanent Ineff=
       F       F
Bank Sta=177.5,194.18
XS Rating Curve= 0 ,0
Exp/Cntr(USF)=0,0
Exp/Cntr=0.3,0.1

Type RM Length L Ch R = 1 ,1298    ,395.3,390.3,385.7
XS GIS Cut Line= 4
2242630.05870312540894.2563706442242661.37564043541031.668894899
2242758.75982537541198.6825550062242967.91429857541172.034546019
#Sta/Elev= 30
       0 2869.14     7.5 2864.07    17.6 2859.13    27.6 2852.66    35.8 2848.21
    44.3 2844.31    56.3 2836.74      61 2834.57    81.5 2819.71    89.2 2815.17
    97.4 2811.65   113.8 2800.79     122 2797.05   134.3 2794.67   137.9 2793.37
   142.7 2789.24   147.3 2786.38   152.9 2786.03   162.4 2786.38   165.8 2786.73
   175.1 2785.75   244.6 2785.78   267.7 2784.88   319.6 2785.36   323.3 2785.74
   332.5 2788.14   380.4 2789.57   440.5 2790.74   468.2 2790.41   545.1 2792.13
#Mann= 6 ,-1,0
       0      .1       0   147.3    .045       0   162.4      .1       0
  170.94     .05       0  290.94     .07       0  344.27     .06       0
#XS Ineff= 2 , 0
                          166.25         2794.47
Permanent Ineff=
       F       F
Bank Sta=147.3,162.4
XS Rating Curve= 0 ,0
Exp/Cntr(USF)=0,0
Exp/Cntr=0.3,0.1

Type RM Length L Ch R = 1 ,908     ,230.1,234,235.7
XS GIS Cut Line= 4
2242198.84324451541116.6996379412242425.73373438541278.433577789
2242505.63183337541275.0086810552242624.10777996541169.693015056
#Sta/Elev= 30
       0 2827.76     6.5 2822.53    16.4 2815.59    21.3 2811.84    31.1 2803.52
    38.6 2798.27    49.1 2789.39    55.8 2784.51    60.6 2781.63    62.8 2780.64
    69.7 2779.01    76.6 2778.57    90.4 2779.31   104.5 2778.74     116 2778.84
   139.2 2778.15   204.9 2777.38   227.9 2777.85   242.2 2777.43   257.1 2777.46
   289.1 2778.46   293.1 2778.38  298.02 2777.23   301.1 2776.87  305.54 2777.23
   313.1  2778.7   329.1  2778.6   345.1 2780.73   367.4 2781.78   517.1 2784.71
#Mann= 7 ,-1,0
       0      .1       0     240     .05       0  298.02    .045       0
  305.54     .05       0  328.63     .06       0  398.61     .05       0
  448.61     .06       0
Bank Sta=298.02,305.54
XS Rating Curve= 0 ,0
Exp/Cntr(USF)=0,0
Exp/Cntr=0.3,0.1

Type RM Length L Ch R = 1 ,674     ,248.2,251.5,254
XS GIS Cut Line= 4
2241985.78544292541208.3666977312242204.87765882541343.192676741
2242327.02736564 541432.815249572242436.74457197541464.722804472
#Sta/Elev= 30
       0 2893.27     8.1 2886.26    26.3 2872.21      31 2868.11    47.3 2852.61
    60.5 2841.37      75 2826.58    98.3 2806.29   108.4 2795.77   120.2 2785.85
   129.6 2777.22   134.3 2774.06     139  2771.9   143.7 2771.21   156.4 2771.09
   171.9 2772.35   182.6 2771.71     306 2772.62   345.7 2773.96   375.5 2774.22
   380.4 2773.86  384.75 2772.59   390.3 2772.59   402.6 2774.03   418.3 2773.99
   451.9 2775.52   472.4 2777.26   506.8  2778.1   514.1 2779.31     523 2782.38
#Mann= 6 ,-1,0
       0      .1       0  277.25     .05       0  384.75    .045       0
   390.3     .05       0  458.76     .06       0  478.76     .05       0
Bank Sta=384.75,390.3
XS Rating Curve= 0 ,0
Exp/Cntr(USF)=0,0
Exp/Cntr=0.3,0.1

Type RM Length L Ch R = 1 ,422     ,379.3,373.4,367.3
XS GIS Cut Line= 5
2241941.75939929541361.6466868872242111.34514285541487.277453933
2242121.02038151541579.8833096132242126.10376865541648.519313811
2242211.94570889541640.030879374
#Sta/Elev= 30
       0 2871.56     7.1 2866.09      13 2862.31    37.9 2841.14    47.1 2829.84
      50 2826.83    72.9 2804.94    84.3 2790.77   107.5 2772.87   112.5  2770.1
   117.5 2768.68   127.2 2769.25   144.4 2768.46   155.8 2769.44   172.3  2769.7
   182.2 2770.71   211.1 2770.49     229 2769.68   241.1 2770.04   257.2 2769.62
   263.12768.447   268.2 2767.95   271.2 2768.46   277.3 2769.77   297.3 2770.19
   357.6 2768.96   395.2 2769.24   415.3 2769.61   436.5 2771.21   459.2 2771.69
#Mann= 3 ,-1,0
       0      .1       0   263.1    .045       0   271.2      .1       0
#XS Ineff= 2 , 0
                          301.32         2778.29
Permanent Ineff=
       F       F
Bank Sta=263.1,271.2
XS Rating Curve= 0 ,0
Exp/Cntr=0.3,0.1

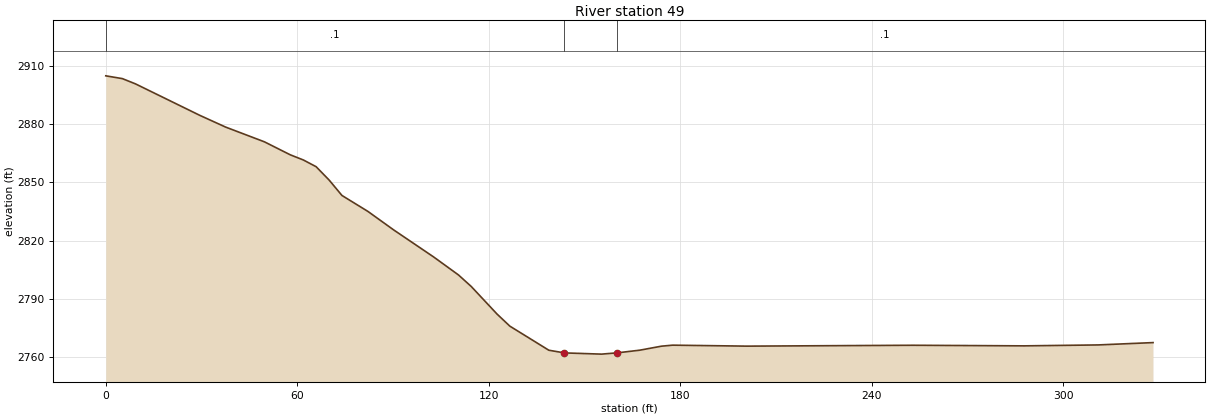
Type RM Length L Ch R = 1 ,49      ,,,
XS GIS Cut Line= 4
2241783.00953583541777.8538356072241917.10548584541798.517068144
2241945.76493873541805.7215203692242063.57431844541693.316895047
#Sta/Elev= 30
       0 2904.75     5.2 2903.31     9.3 2900.61    29.5 2884.38    37.6 2878.34
    49.7 2870.79    57.8 2864.11    61.9 2861.45    65.9 2857.99      70 2851.07
      74 2843.18    82.1 2835.01    90.2 2825.46   102.7 2811.57   110.5 2802.29
   114.5 2796.35   122.6 2782.13   126.6 2775.94   138.8 2763.56   143.7 2762.18
   155.3 2761.55   160.2  2762.2   167.3 2763.58   174.1 2765.64   177.6 2766.16
   200.8 2765.66   252.9 2766.11   287.7  2765.8   310.9 2766.28   328.1 2767.48
#Mann= 3 ,-1,0
       0      .1       0   143.7    .045       0   160.2      .1       0
Bank Sta=143.7,160.2
XS Rating Curve= 0 ,0
Exp/Cntr=0.3,0.1
LCMann Table=0

Chan Stop Cuts=-1
Use User Specified Reach Order=0
Composite Channel Slope=5